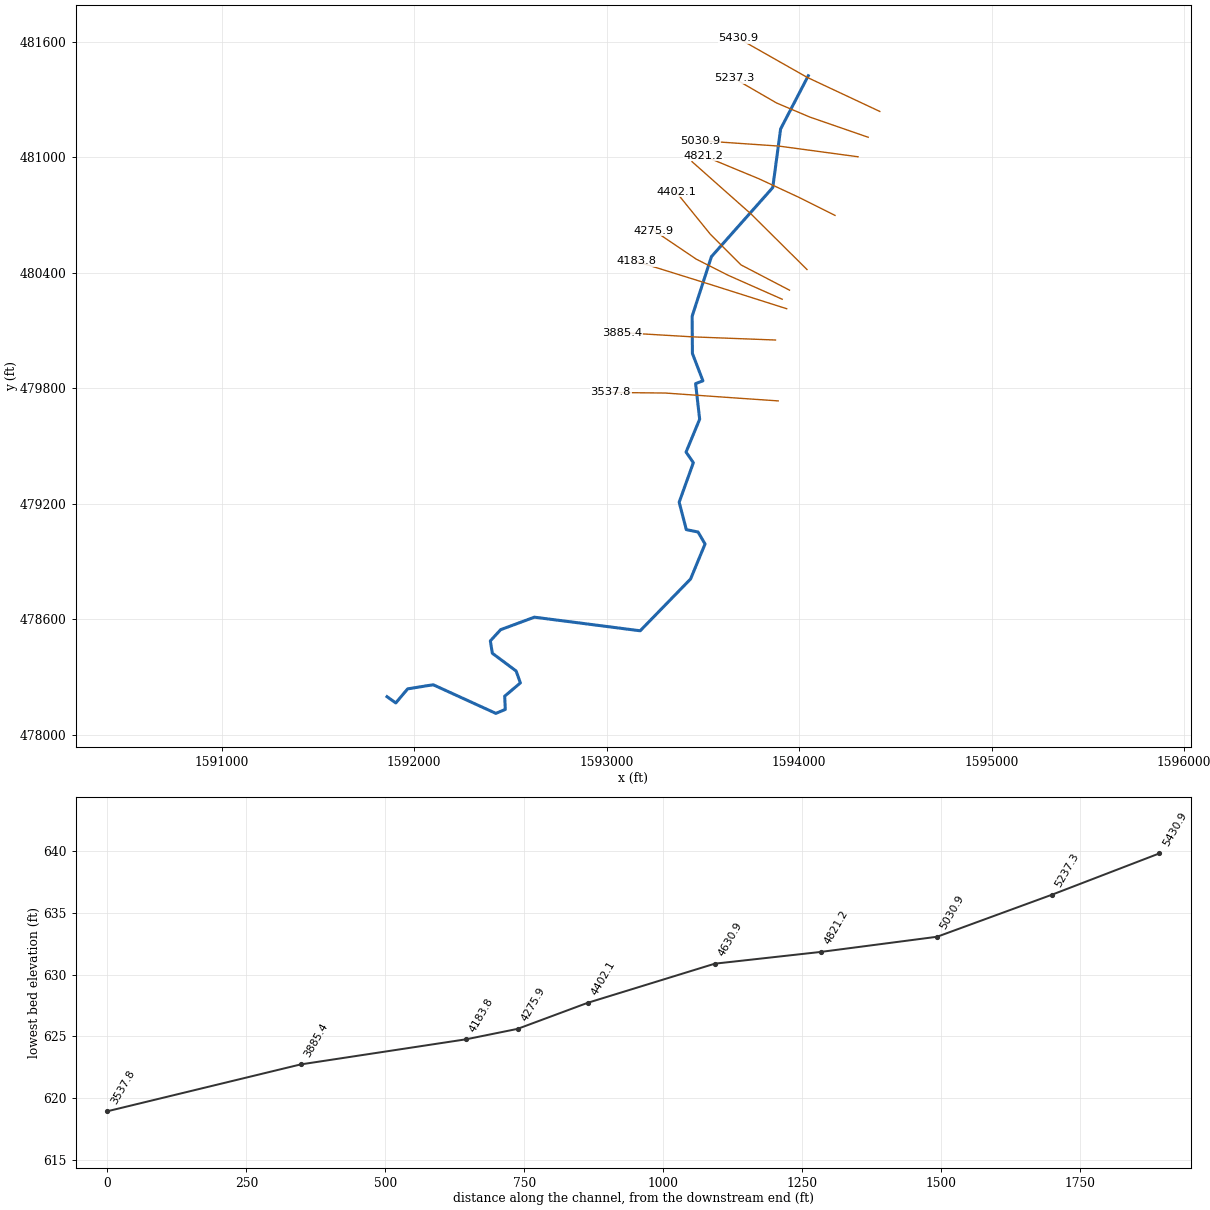
--- GRASYLICK.prj (project) ---

Proj Title=GRASYLICK
Current Plan=p01
Default Exp/Contr=0,0
English Units
Geom File=g01
Flow File=f01
Plan File=p01
BEGIN DESCRIPTION:
END DESCRIPTION:
DSS Export Rating Curves= 0
DSS Export Rating Curve Sorted= 0
DSS Export Volume Flow Curves= 0
DXF OffsetX= 0
DXF OffsetY= 0
DXF ScaleX= 0
DXF ScaleY= 0

--- GRASYLICK.p01 (plan) ---

Plan Title=Floodplain
Program Version=4.00
Geom File=g01
Flow File=f01
K Sum by GR=0
Std Step Tol=0.01
Critical Tol=0.01
Num of Std Step Trials=20
Max Error Tol=0.3
Flow Tol Ratio=0.001
Split Flow NTrial=30
Split Flow Tol=0.02
Split Flow Ratio=0.02
Log Output Level=0
Friction Slope Method=1
Unsteady Friction Slope Method=2
Unsteady Bridges Friction Slope Method=1
Global Log Level=0
CheckData=False
Run HTab=0
Run UNet=0
Run PostProcess=0
UNET Theta=0
UNET Theta Warmup=0
UNET ZTol=0
UNET ZSATol=0
UNET MxIter=0
UNET MaxInSteps=0
UNET DtIC=0
UNET DtMin=0
UNET MaxCRTS=0
UNET WFStab=0
UNET SFStab=0
UNET WFX=0
UNET SFX=0
UNET DSS MLevel=0
UNET DZMax Abort=0
UNET Convert EG Bridges=0
UNET Use Existing IB Tables=0
UNET Froude Limit=0
UNET Froude Power=0
Write IC File=0
Echo Input=False
Echo Output=False
Write Detailed=0

--- GRASYLICK.f01 (steady flow) ---

Flow Title=NFF Regression Equation
Program Version=4.00
Number of Profiles=1
Profile Names=P100yr
River Rch & RM=GRASYLICK,Main      ,5430.9
     371
River Rch & RM=GRASYLICK,Main      ,4183.8
     379
River Rch & RM=GRASYLICK,Main      ,3885.4
     447
Boundary for River Rch & Prof#=GRASYLICK,Main      ,1
Up Type=0
Dn Type=3
Dn Slope=0.008962

--- GRASYLICK.g01 (geometry) ---

Geom Title=USGS 10m DEM
Program Version=4.00

River Reach=GRASYLICK       ,Main
Reach XY= 30
      1594046.76      481422.452     1593903.087      481146.261
     1593862.286      480841.697     1593543.694      480482.805
     1593443.459       480173.28     1593444.913      479979.663
     1593499.434      479837.802     1593461.417      479823.076
     1593482.525      479638.217     1593411.856      479467.475
     1593449.757      479412.481     1593376.094       479206.92
     1593413.196      479064.572     1593474.022      479052.359
      1593510.52      478989.998     1593435.365      478808.207
     1593173.526       478539.12     1592623.849      478609.768
     1592448.544      478544.784     1592395.091      478486.503
     1592405.298      478422.437     1592529.022      478330.086
     1592551.191      478268.293     1592469.635      478199.236
     1592472.753      478130.508      1592423.73      478110.017
      1592098.08      478258.768     1591965.192      478237.205
     1591903.879       478164.14     1591858.252      478196.655

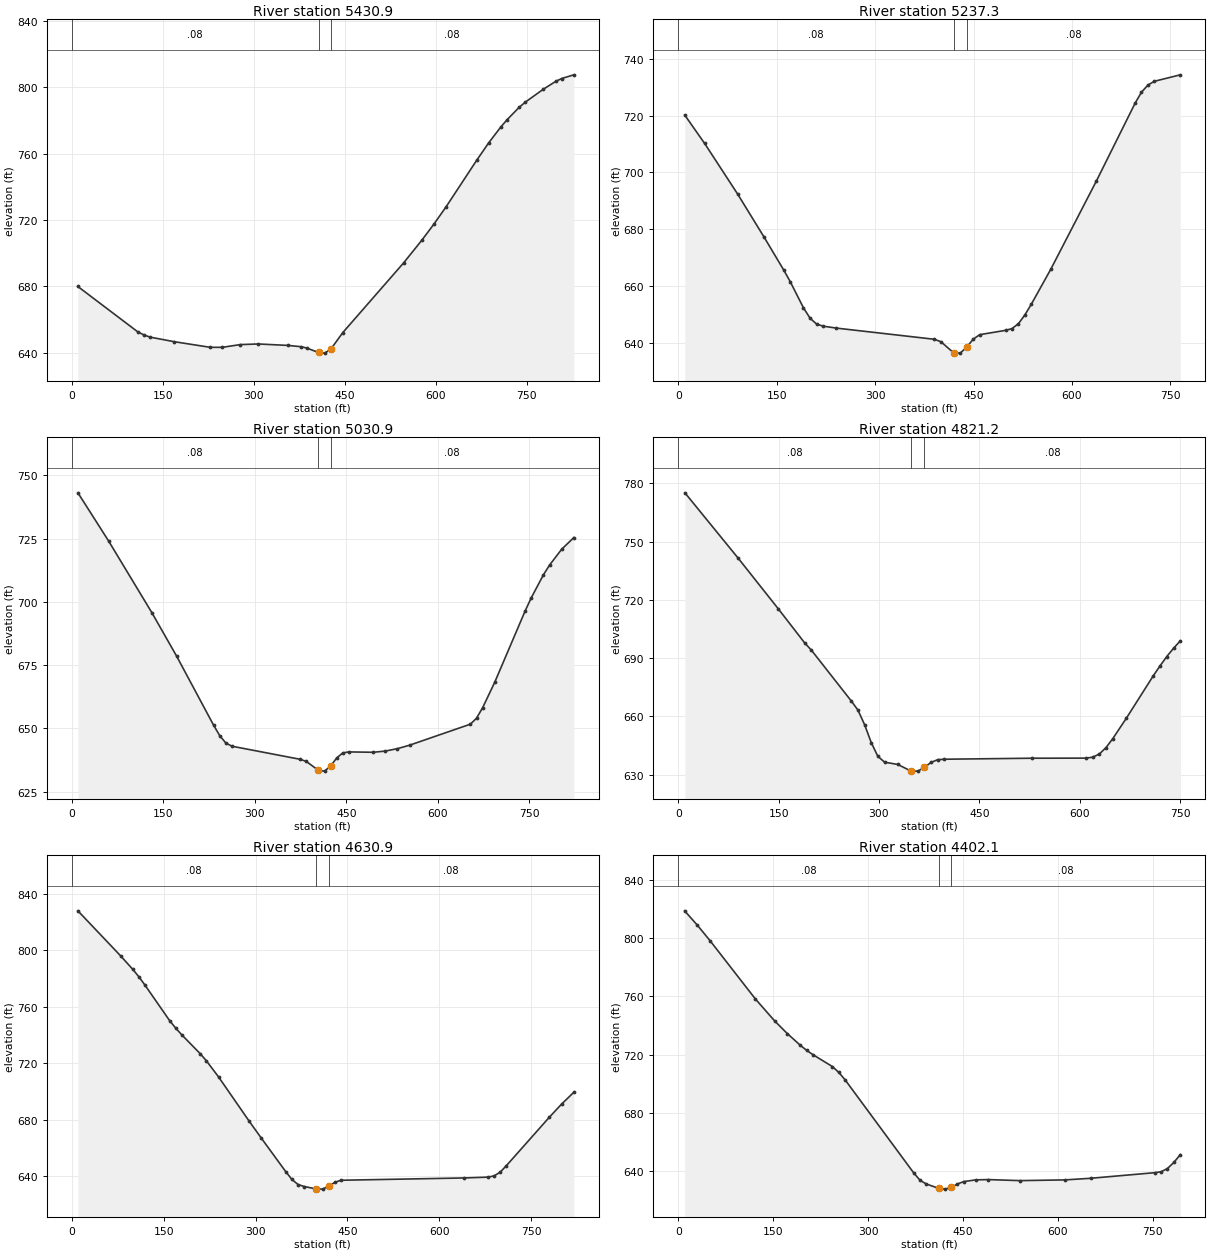
Type RM Length L Ch R = 1 ,5430.9  ,192.3,193.6,196.6
XS GIS Cut Line= 3
     1594418.443       481237.22     1594041.034      481414.254
     1593683.522      481617.001
#Sta/Elev= 30
     9.9  680.01   109.2  652.53   119.1  650.77     129  649.46   168.7  646.72
   228.3  643.31   248.1   643.3   277.9  644.95   307.7  645.33   357.3  644.44
   377.2  643.71   387.1  642.92   406.9  640.19   416.9  639.81   426.9  642.08
   446.9  652.19   547.2   694.2   577.3  707.89   597.3  717.63   617.4  728.09
   667.5  755.93   687.5  766.56   707.6  776.15   717.6  780.41   737.6  787.91
   747.7  791.03   777.7   798.9   797.8  803.53   807.8  805.32   827.9  807.54
#Mann= 3 , 0 , 0
       0     .08       0   406.9    .045       0   426.9     .08       0
Bank Sta=406.9,426.9
XS Rating Curve= 0 ,0
Exp/Cntr=0.3,0.1

Type RM Length L Ch R = 1 ,5237.3  ,199.7,206.4,214.7
XS GIS Cut Line= 4
     1594358.122       481103.02     1594054.406      481208.153
     1593882.105      481281.161     1593660.159      481409.657
#Sta/Elev= 30
      10  720.16    40.2  710.21    90.4  692.44   130.6  677.34   160.7   665.7
   170.7  661.57   190.8   652.4   200.9  648.73   210.9  646.67     221  645.94
     241  645.26   390.3  641.33   400.2  640.48   419.7  636.55   429.7  636.46
   439.7  638.61   449.4  641.36   459.3  642.95   498.7  644.47   508.5  645.08
   518.4  646.82   528.3  649.95   538.1  653.71   567.7  665.99   636.8  696.84
   695.9  724.26   705.8  728.21   715.7  730.74   725.5  732.06     765  734.33
#Mann= 3 , 0 , 0
       0     .08       0   419.7    .045       0   439.7     .08       0
Bank Sta=419.7,439.7
XS Rating Curve= 0 ,0
Exp/Cntr=0.3,0.1

Type RM Length L Ch R = 1 ,5030.9  ,217.2,209.6,200.4
XS GIS Cut Line= 3
     1594305.618      481001.628     1593895.034       481057.14
     1593487.344      481085.137
#Sta/Elev= 30
    10.1  743.08    60.6  723.95   131.4  695.66   171.8  678.55   232.4  651.26
   242.5   647.1   252.6  644.15   262.7   642.9   373.9  637.76     384  636.97
   404.3  633.38   414.3  633.06   424.3  635.06   434.3  638.27   444.2  640.26
   454.2  640.66   494.1  640.51     514  640.99   533.9  641.95   553.9  643.33
   653.5  651.63   663.5     654   673.5  658.14   693.4  668.24   743.2   696.4
   753.2  701.58   773.1  710.66   783.1  714.49     803  720.76     823  725.41
#Mann= 3 , 0 , 0
       0     .08       0   404.3    .045       0   424.3     .08       0
Bank Sta=404.3,424.3
XS Rating Curve= 0 ,0
Exp/Cntr=0.3,0.1

Type RM Length L Ch R = 1 ,4821.2  ,199.1,190.4,183.1
XS GIS Cut Line= 4
     1594185.821      480697.092     1593998.919      480790.543
     1593791.574      480886.915      1593502.46      481006.649
#Sta/Elev= 30
      10  775.17    89.6  741.51   149.3  715.54   189.1  697.83     199  694.15
   258.7  667.95   268.6  663.28   278.6  655.74   288.5  646.54   298.4  639.45
   308.4  636.46   328.3  635.25   348.1  631.84   358.1  631.83   368.1   633.8
     378  636.34   387.9  637.73   397.8  637.96   528.5  638.48   609.2  638.53
   619.3  638.99   629.4  640.62   639.5  643.97   649.6  648.59   669.8  659.06
   710.2  680.98   720.3  686.09   730.3  690.86   740.4  695.11   750.5  698.94
#Mann= 3 , 0 , 0
       0     .08       0   348.1    .045       0   368.1     .08       0
Bank Sta=348.1,368.1
XS Rating Curve= 0 ,0
Exp/Cntr=0.3,0.1

Type RM Length L Ch R = 1 ,4630.9  ,228.3,228.8,227.7
XS GIS Cut Line= 3
     1594040.112      480415.953     1593749.539      480704.299
     1593442.541      480976.488
#Sta/Elev= 30
      10  827.92    79.9  795.97    99.8  786.38   109.8  781.09   119.8  775.15
   159.8  750.16   169.7  744.84   179.7  740.07   209.7  726.77   219.7  721.76
   239.6  710.34   289.5  679.06   309.5  666.95   349.5  643.15   359.4  637.73
   369.4  634.14   379.4  632.74   399.4  630.99   409.4  630.88   419.4  632.99
   429.4  635.68   439.4  637.16   639.5  638.78   679.5  639.37   689.6  640.28
   699.6     643   709.6  647.55   779.6  681.79   799.6  691.08   819.6  699.47
#Mann= 3 , 0 , 0
       0     .08       0   399.4    .045       0   419.4     .08       0
Bank Sta=399.4,419.4
XS Rating Curve= 0 ,0
Exp/Cntr=0.3,0.1

Type RM Length L Ch R = 1 ,4402.1  ,118.2,126.2,134.2
XS GIS Cut Line= 4
     1593949.273      480308.686     1593697.406      480439.885
      1593537.89      480599.401     1593359.363      480819.747
#Sta/Elev= 30
    10.1  818.58    30.4  808.63    50.7  797.86   121.7  758.23   152.1  743.17
   172.4  734.37   192.7  726.42   202.8  722.91     213  719.88   243.4  711.81
   253.6  707.81   263.7  702.63   372.3  638.67   382.1  633.76   391.9  631.24
   411.3  628.28   421.3  627.71   431.3  628.86   440.9  631.18   450.7  632.86
   470.3  634.07     490  634.25     540  633.54   610.9  634.04   651.4  635.14
   752.7  638.98   762.8  639.62   772.9  641.84     783  646.03   793.2  651.37
#Mann= 3 , 0 , 0
       0     .08       0   411.3    .045       0   431.3     .08       0
Bank Sta=411.3,431.3
XS Rating Curve= 0 ,0
Exp/Cntr=0.3,0.1

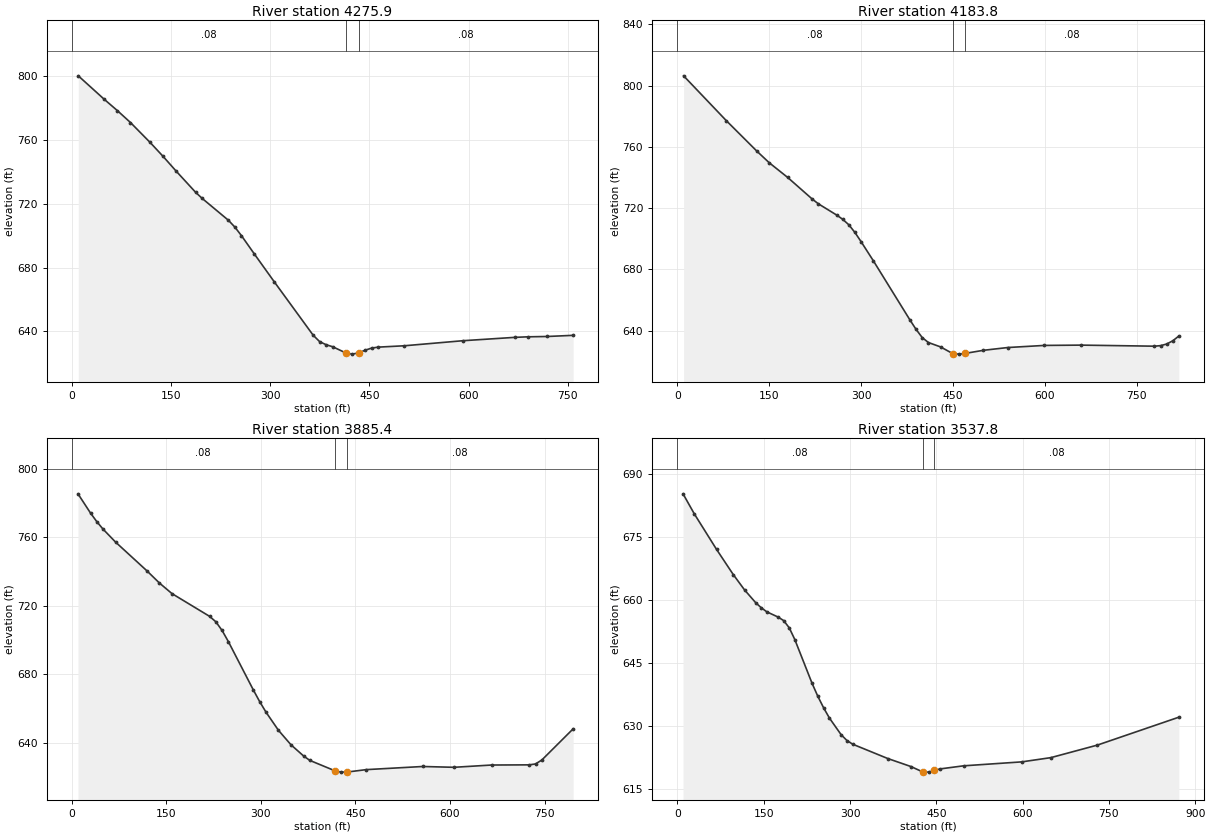
Type RM Length L Ch R = 1 ,4275.9  ,87.9,92.1,96.3
XS GIS Cut Line= 4
     1593911.345      480261.602     1593631.723      480385.461
     1593464.701      480469.911     1593245.132      480618.167
#Sta/Elev= 30
     9.9  800.41    49.3   785.6    69.1  778.52    88.8  771.07   118.4   758.6
   138.1   749.8   157.8  740.57   187.4  727.18   197.3  723.37   236.8  709.69
   246.6  705.39   256.5  700.04   276.2  688.41   305.8  671.22   364.9   637.5
   374.8  633.42   384.6   631.5   394.5  630.23     414  626.41     424   625.6
     434  626.42   443.7   628.1   453.6  629.42   463.4     630   502.8  630.85
   591.1  634.02   669.6  636.13   689.2  636.47   718.7  636.68   757.9   637.4
#Mann= 3 , 0 , 0
       0     .08       0     414    .045       0     434     .08       0
Bank Sta=414,434
XS Rating Curve= 0 ,0
Exp/Cntr=0.3,0.1

Type RM Length L Ch R = 1 ,4183.8  ,291.4,298.4,304.9
XS GIS Cut Line= 3
     1593934.671      480212.315     1593544.214      480336.359
     1593153.704      480458.128
#Sta/Elev= 30
      10  806.34    79.9  777.03   129.9   757.1   149.9   749.6   179.9  740.06
   219.8  726.03   229.8   722.9   259.8  715.54   269.8  712.73   279.8  709.15
   289.8  704.12   299.8  698.15   319.8  685.69   379.7  646.99   389.7  640.85
   399.7  635.54   409.7  632.34   429.6  629.47   449.6  625.08   459.6  624.76
   469.6  625.23   499.5  627.25   539.4  629.07   599.2  630.44   659.1  630.64
   778.8  629.94   788.8   630.3   798.8  631.34   808.8  633.47   818.7  636.58
#Mann= 3 , 0 , 0
       0     .08       0   449.6    .045       0   469.6     .08       0
Bank Sta=449.6,469.6
XS Rating Curve= 0 ,0
Exp/Cntr=0.3,0.1

Type RM Length L Ch R = 1 ,3885.4  ,350,347.5,338.9
XS GIS Cut Line= 3
     1593876.507      480049.688     1593449.518      480065.898
     1593082.173      480087.652
#Sta/Elev= 30
     9.9  785.36    29.8  774.12    39.7  769.13    49.7  764.71    69.6  757.13
   119.2  740.38   139.1  733.23     159  727.05   218.6  713.77   228.6  710.58
   238.5  705.49   248.4  699.02   288.2  670.63   298.1  663.93   308.1  657.78
   327.9  647.16   347.8  638.68   367.7  632.18   377.6  629.58   417.3  623.53
   427.3  622.72   437.3  622.79   467.1  624.18   556.6  626.01   606.3  625.54
     666  626.87   725.7  626.97   735.6   627.5   745.6  629.79   795.3  648.02
#Mann= 3 , 0 , 0
       0     .08       0   417.3    .045       0   437.3     .08       0
Bank Sta=417.3,437.3
XS Rating Curve= 0 ,0
Exp/Cntr=0.3,0.1

Type RM Length L Ch R = 1 ,3537.8  ,3591.1,3537.8,3473.2
XS GIS Cut Line= 4
     1593890.866      479733.378     1593677.681       479747.98
     1593303.877      479774.263     1593020.603      479777.183
#Sta/Elev= 30
     9.7  685.19    29.1  680.46      68  671.95    97.1  665.95   116.6  662.32
     136  659.27   145.7  658.06   155.4  657.09   174.8  655.86   184.5  655.02
   194.3   653.3     204   650.5   233.9  640.11   244.1  636.96   254.2  634.21
   264.3  631.78   284.6  627.83   294.7  626.45   304.8  625.57   365.6  622.17
   406.1  620.25   426.5  618.97   436.5  618.93   446.5  619.32   456.8   619.7
   497.3  620.43   598.5  621.37   649.1  622.38   730.1  625.37   871.7  632.01
#Mann= 3 , 0 , 0
       0     .08       0   426.5    .045       0   446.5     .08       0
Bank Sta=426.5,446.5
XS Rating Curve= 0 ,0
Exp/Cntr=0.3,0.1

Chan Stop Cuts=-1
Use User Specified Reach Order=0